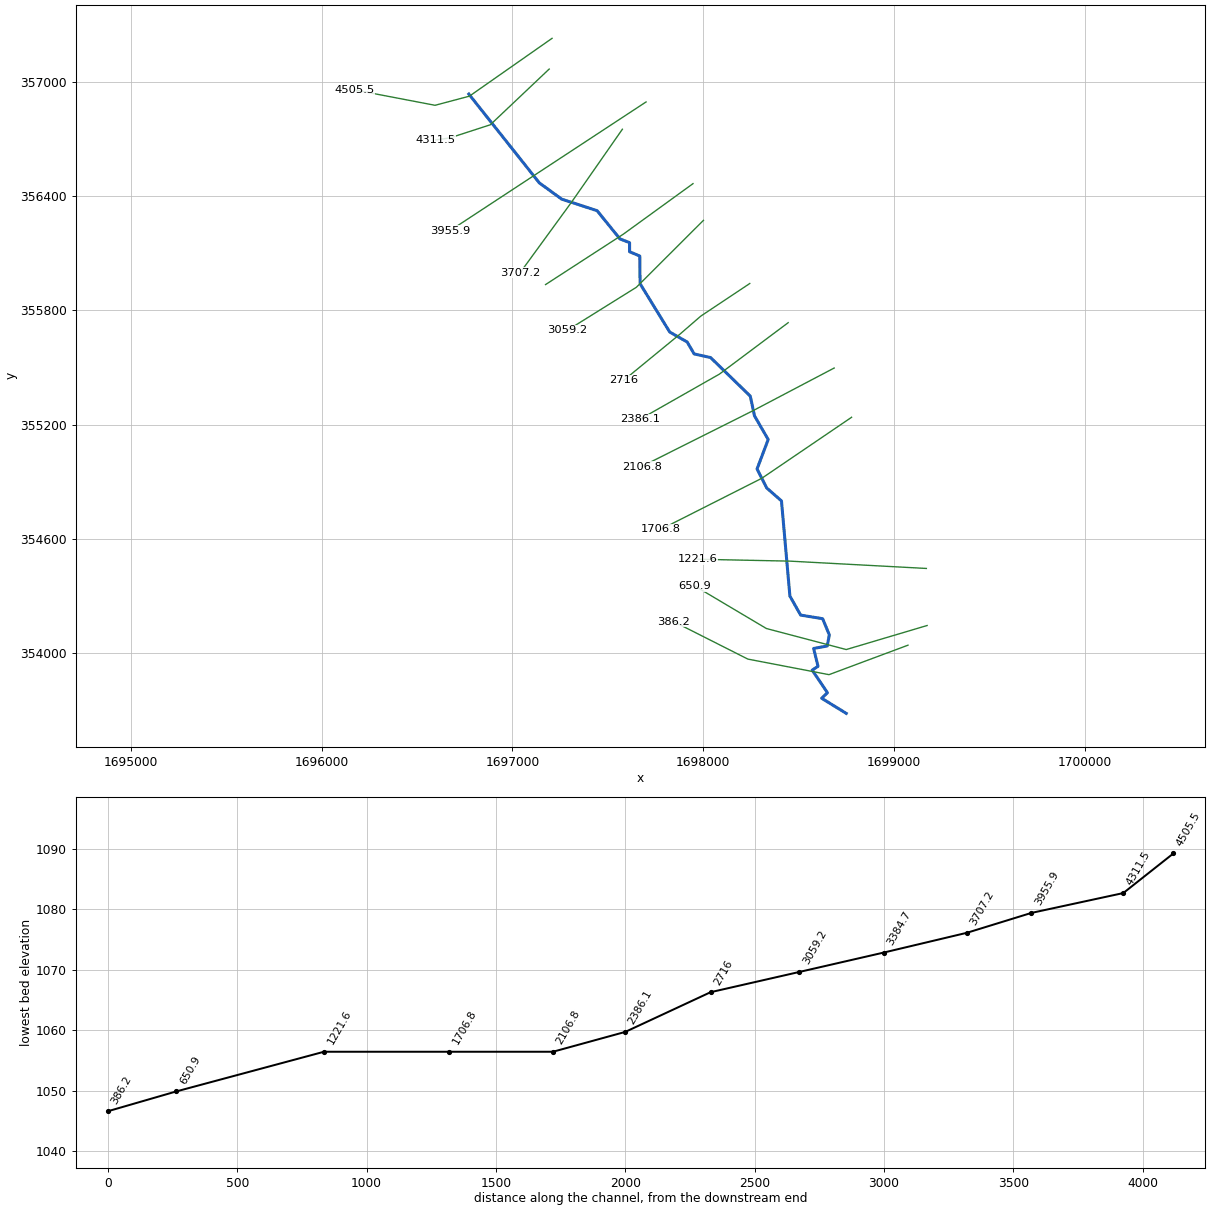
--- WlfptRn.prj (project) ---

Proj Title=WlfptRn
Current Plan=p01
Geom File=g01
Flow File=f01
Plan File=p01
DSS Export Rating Curves=0
DSS Export Rating Curve Sorted=0
DSS Export Volume Flow Curves=0
DXF OffsetX=0
DXF OffsetY=0
DXF ScaleX=0
DXF ScaleY=0

--- WlfptRn.p01 (plan) ---

Plan Title=Floodplain
Program Version=4.00
Geom File=g01
Flow File=f01
K Sum by GR=0
Std Step Tol=0.01
Critical Tol=0.01
Num of Std Step Trials=20
Max Error Tol=0.3
Flow Tol Ratio=0.001
Split Flow NTrial=30
Split Flow Tol=0.02
Split Flow Ratio=0.02
Log Output Level=0
Friction Slope Method=1
Unsteady Friction Slope Method=2
Unsteady Bridges Friction Slope Method=1
Global Log Level=0
CheckData=False
Run HTab=0
Run UNet=0
Run PostProcess=0
UNET Theta=0
UNET Theta Warmup=0
UNET ZTol=0
UNET ZSATol=0
UNET MxIter=0
UNET MaxInSteps=0
UNET DtIC=0
UNET DtMin=0
UNET MaxCRTS=0
UNET WFStab=0
UNET SFStab=0
UNET WFX=0
UNET SFX=0
UNET DSS MLevel=0
UNET DZMax Abort=0
UNET Convert EG Bridges=0
UNET Use Existing IB Tables=0
UNET Froude Limit=0
UNET Froude Power=0
Write IC File=0
Echo Input=False
Echo Output=False
Write Detailed=0

--- WlfptRn.f01 (steady flow) ---

Flow Title=NFF Regression Equation
Program Version=4.00
Number of Profiles=1
Profile Names=P100yr
River Rch & RM=WlfptRn,Main      ,4505.5
431.2680
River Rch & RM=WlfptRn,Main      ,3955.9
483.9872
River Rch & RM=WlfptRn,Main      ,3059.2
517.0432
River Rch & RM=WlfptRn,Main      ,2716
584.1514
River Rch & RM=WlfptRn,Main      ,2106.8
594.0086
River Rch & RM=WlfptRn,Main      ,650.9
655.5594
River Rch & RM=WlfptRn,Main      ,386.2
655.5594
Boundary for River Rch & Prof#=WlfptRn,Main      ,1
Up Type=0
Dn Type=3
Dn Slope=0.008327

--- WlfptRn.g01 (geometry) ---

Geom Title=USGS 3m DEM
Program Version=4.00

River Reach=WlfptRn     ,Main
Reach XY= 30
     1696771.484      356935.933     1697141.006      356469.426
     1697258.214      356384.088     1697444.303      356323.051
     1697563.731      356175.163     1697614.251      356155.327
     1697614.263      356107.759     1697667.780      356084.961
     1697669.305      355939.676     1697824.661      355685.828
     1697916.386      355633.434     1697952.727      355570.885
     1698038.845      355551.769     1698247.002      355349.265
     1698269.087      355245.528     1698340.976      355121.232
     1698282.584      354966.571     1698333.060      354866.807
     1698410.566      354798.690     1698454.747      354298.849
     1698510.903      354198.902     1698626.558      354179.780
     1698661.387      354094.776     1698650.164      354036.398
     1698579.036      354023.659     1698602.220      353929.681
     1698571.530      353909.857     1698651.672      353791.154
     1698621.355      353761.922     1698750.144      353682.575

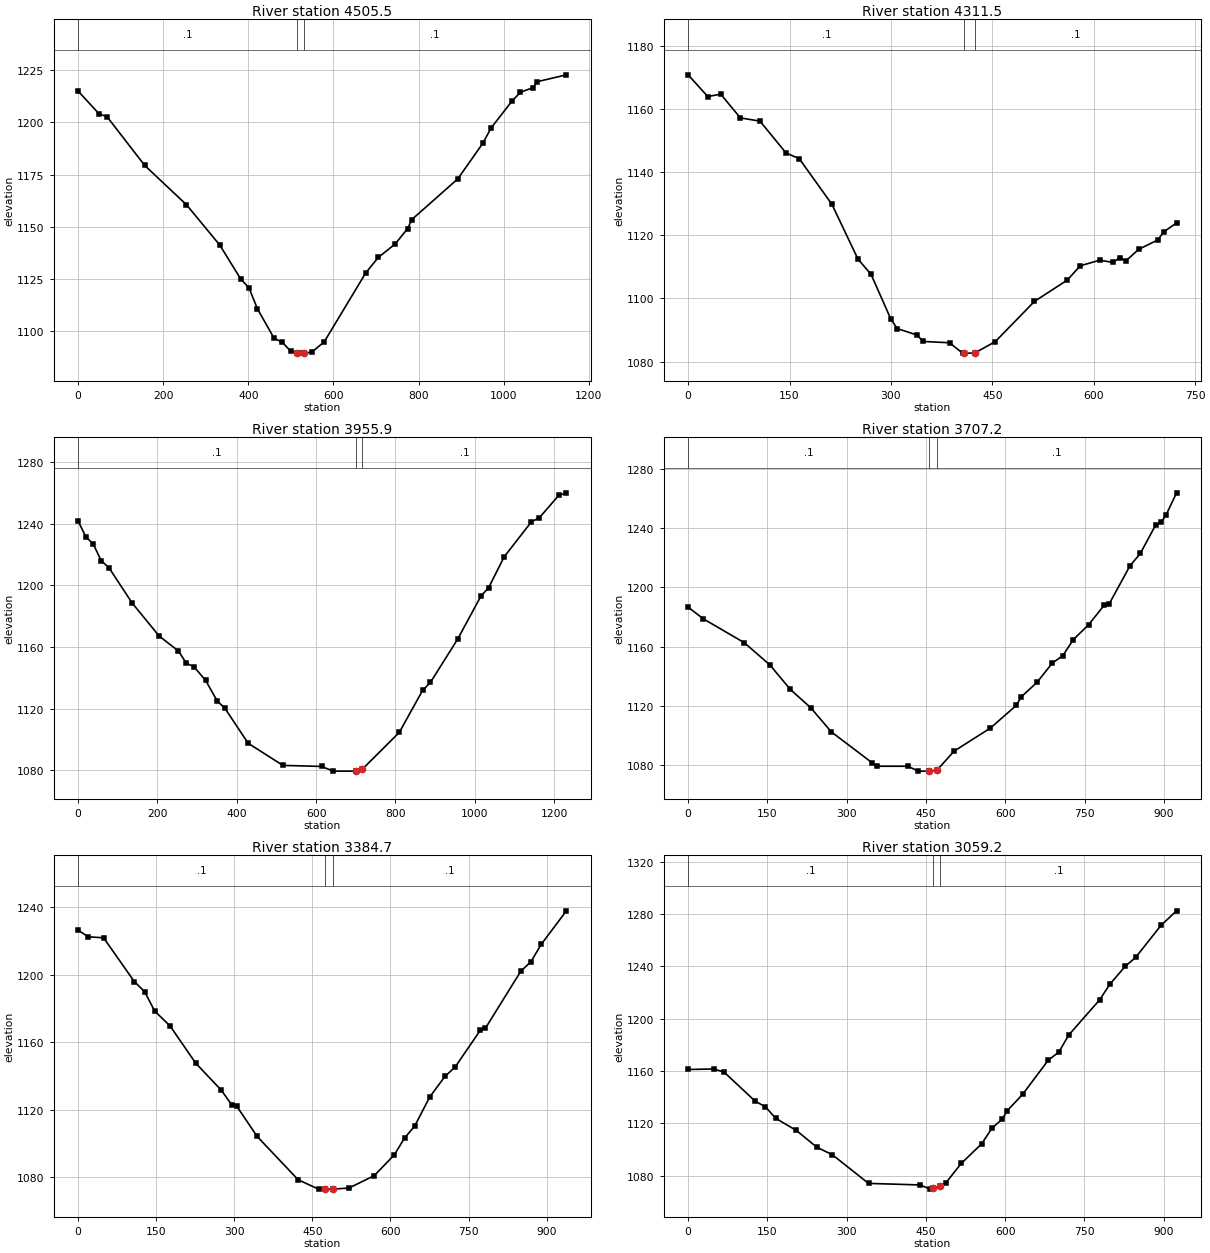
Type RM Length L Ch R = 1 ,4505.5,190.487,193.991,197.235
XS GIS Cut Line= 4
     1697207.900      357228.709     1696774.603      356924.895
     1696594.595      356876.960     1696170.693      356958.133
#Sta/Elev= 30
       0 1215.13    49.0 1204.29    68.6 1202.68   156.8 1179.36   254.8 1160.50
   333.2 1141.08   382.2 1124.84   401.8 1120.52   421.4 1110.53   460.6 1096.40
   480.2 1094.37   499.8 1090.13   514.9 1089.28   519.4 1089.24   529.9 1089.24
   548.8 1089.69   578.2 1094.62   676.3 1127.92   705.7 1135.25   744.9 1141.64
   774.3 1149.07   784.1 1153.39   892.0 1172.93   950.9 1190.05   970.5 1197.46
  1019.6 1210.34  1039.2 1214.53  1068.6 1216.71  1078.4 1219.58  1147.1 1222.88
#Mann= 3 , 0 , 0
       0     0.1       0   514.9   0.045       0   529.9     0.1       0
Bank Sta=   514.9,   529.9
Exp/Cntr=0.3,0.1

Type RM Length L Ch R = 1 ,4311.5,359.541,355.69,359.105
XS GIS Cut Line= 4
     1697192.753      357067.256     1696884.169      356774.542
     1696672.568      356705.771     1696598.507      356695.191
#Sta/Elev= 30
       0 1170.83    29.0 1163.96    48.3 1164.69    77.3 1157.19   106.3 1156.16
   145.0 1146.05   164.3 1144.30   212.7 1129.83   251.3 1112.45   270.7 1107.61
   299.7 1093.55   309.3 1090.46   338.3 1088.44   348.0 1086.38   386.7 1085.96
   406.0 1082.68   408.8 1082.68   423.8 1082.68   454.4 1086.32   512.4 1099.07
   560.8 1105.80   580.1 1110.34   609.1 1112.13   628.5 1111.39   638.2 1112.86
   647.8 1111.94   666.5 1115.54   694.6 1118.51   703.9 1121.14   722.6 1123.91
#Mann= 3 , 0 , 0
       0     0.1       0   408.8   0.045       0   423.8     0.1       0
Bank Sta=   408.8,   423.8
Exp/Cntr=0.3,0.1

Type RM Length L Ch R = 1 ,3955.9,241.26,248.671,255.999
XS GIS Cut Line= 3
     1697700.643      356894.577     1697147.160      356530.329
     1696672.455      356218.138
#Sta/Elev= 30
       0 1241.89    19.5 1231.65    39.0 1226.50    58.5 1215.98    78.0 1211.43
   136.4 1188.53   204.6 1167.06   253.3 1157.32   272.8 1149.49   292.3 1147.10
   321.5 1138.35   350.8 1124.92   370.3 1120.16   428.7 1097.50   516.4 1083.10
   613.9 1082.44   643.1 1079.39   701.7 1079.39   716.7 1080.70   809.5 1104.49
   868.3 1131.76   887.9 1136.91   956.5 1164.99  1015.2 1192.93  1034.8 1198.52
  1074.0 1218.51  1142.6 1241.22  1162.2 1243.72  1211.2 1258.30  1230.7 1260.00
#Mann= 3 , 0 , 0
       0     0.1       0   701.7   0.045       0   716.7     0.1       0
Bank Sta=   701.7,   716.7
Exp/Cntr=0.3,0.1

Type RM Length L Ch R = 1 ,3707.2,330.504,322.472,314.994
XS GIS Cut Line= 3
     1697576.420      356751.121     1697311.450      356370.095
     1697041.059      355998.375
#Sta/Elev= 30
       0 1186.57    29.0 1178.68   106.4 1162.60   154.7 1147.65   193.4 1131.12
   232.1 1118.76   270.7 1102.60   348.1 1081.71   357.7 1079.42   415.8 1079.39
   435.1 1076.11   455.8 1076.11   470.8 1076.81   503.2 1089.64   571.7 1105.11
   620.6 1120.39   630.4 1126.26   659.7 1135.88   689.0 1149.00   708.6 1153.85
   728.2 1164.59   757.5 1174.78   786.8 1187.83   796.6 1188.93   835.7 1214.45
   855.3 1222.81   884.6 1242.17   894.4 1243.66   904.2 1248.90   923.8 1263.62
#Mann= 3 , 0 , 0
       0     0.1       0   455.8   0.045       0   470.8     0.1       0
Bank Sta=   455.8,   470.8
Exp/Cntr=0.3,0.1

Type RM Length L Ch R = 1 ,3384.7,312.85,325.539,331.724
XS GIS Cut Line= 3
     1697946.778      356465.402     1697580.960      356199.604
     1697173.723      355935.153
#Sta/Elev= 30
       0 1226.50    19.7 1222.48    49.2 1221.90   108.1 1195.98   127.8 1189.99
   147.5 1178.39   176.9 1169.58   226.1 1147.53   275.2 1131.51   294.9 1122.99
   304.7 1122.06   344.1 1104.05   422.7 1078.40   461.9 1072.83   474.8 1072.83
   489.8 1072.83   520.2 1073.47   568.7 1080.80   607.6 1093.24   627.0 1103.15
   646.4 1110.19   675.5 1127.56   704.7 1139.72   724.1 1145.23   772.7 1167.16
   782.4 1168.32   850.4 1202.15   869.8 1207.74   889.2 1217.93   937.8 1237.90
#Mann= 3 , 0 , 0
       0     0.1       0   474.8   0.045       0   489.8     0.1       0
Bank Sta=   474.8,   489.8
Exp/Cntr=0.3,0.1

Type RM Length L Ch R = 1 ,3059.2,347.635,343.153,339.86
XS GIS Cut Line= 3
     1698001.589      356272.674     1697649.841      355920.926
     1697287.771      355694.665
#Sta/Elev= 30
       0 1161.14    48.8 1161.54    68.3 1159.07   126.8 1136.93   146.3 1132.59
   165.8 1123.79   204.8 1114.52   243.8 1101.61   273.1 1095.91   341.4 1074.02
   438.9 1072.83   458.4 1069.63   462.6 1070.19   477.6 1072.11   487.7 1074.36
   516.9 1089.29   555.7 1104.36   575.1 1116.29   594.5 1123.22   604.2 1129.73
   633.3 1142.25   681.8 1168.38   701.2 1174.26   720.6 1187.62   778.8 1214.41
   798.3 1226.41   827.4 1240.14   846.8 1246.81   895.3 1271.54   924.4 1282.51
#Mann= 3 , 0 , 0
       0     0.1       0   462.6   0.045       0   477.6     0.1       0
Bank Sta=   462.6,   477.6
Exp/Cntr=0.3,0.1

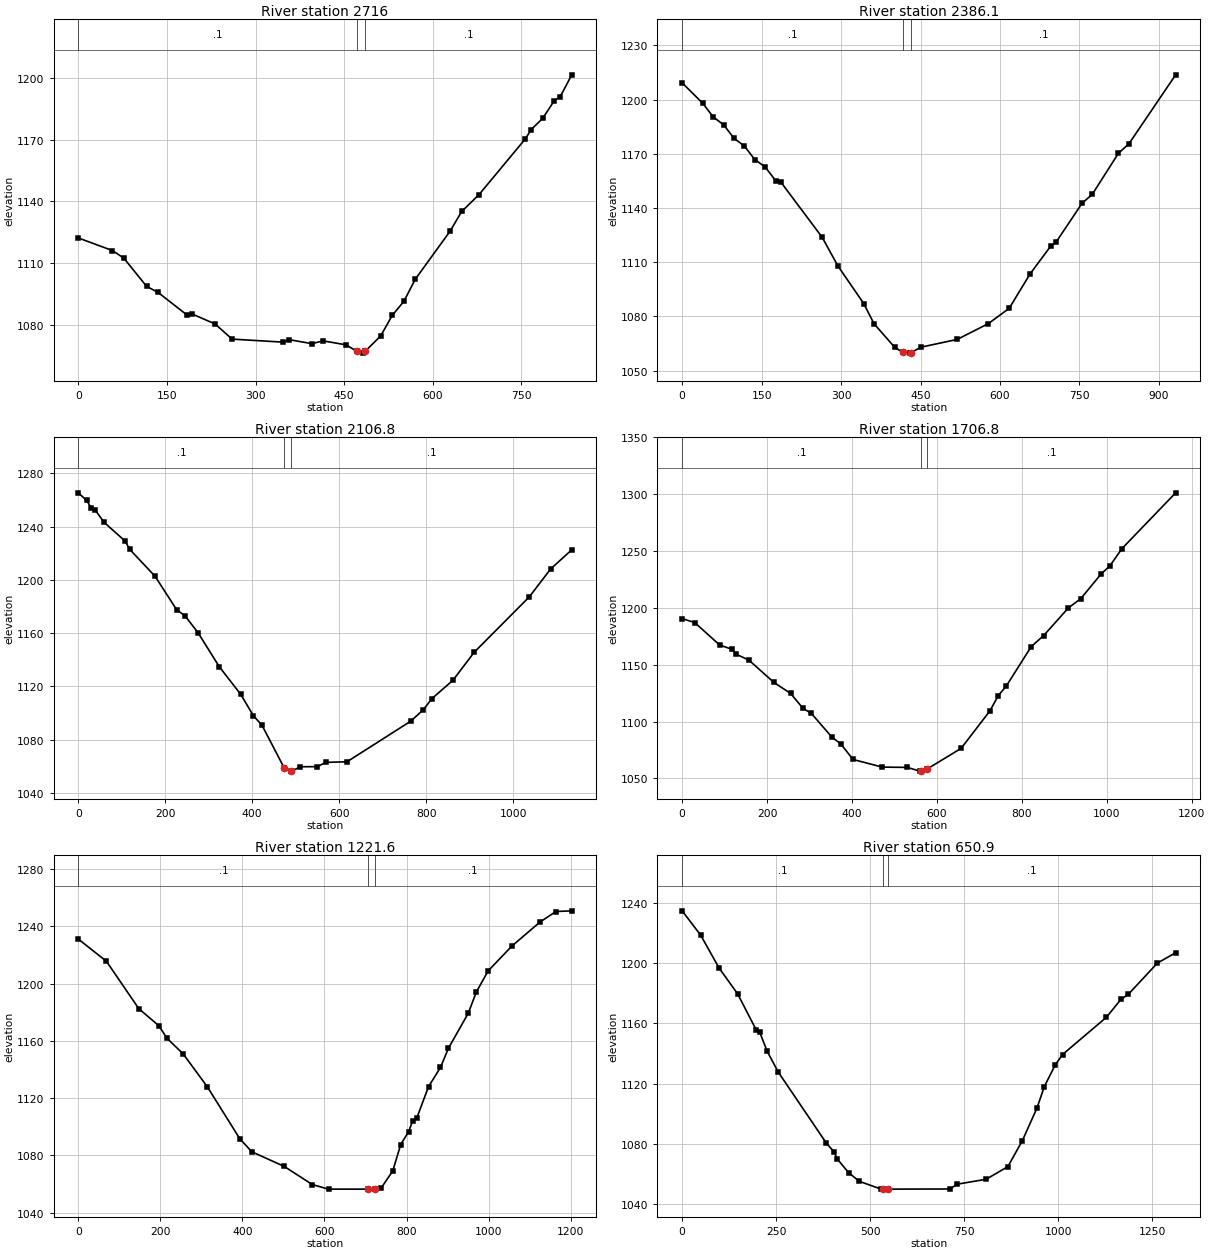
Type RM Length L Ch R = 1 ,2716,330.389,329.907,328.751
XS GIS Cut Line= 4
     1698244.439      355940.762     1697987.647      355769.542
     1697878.622      355674.963     1697583.494      355432.225
#Sta/Elev= 30
       0 1122.23    57.9 1116.10    77.2 1112.41   115.7 1098.71   135.0 1095.79
   183.3 1084.97   192.9 1085.27   231.5 1080.45   260.4 1073.09   347.1 1071.61
   356.7 1072.83   395.2 1070.89   414.5 1072.22   453.0 1070.33   471.1 1067.22
   482.4 1066.28   486.1 1067.32   511.8 1074.63   531.4 1084.62   551.0 1091.41
   570.5 1102.22   629.3 1125.53   648.9 1135.07   678.3 1143.29   756.7 1170.37
   766.5 1174.88   786.1 1180.33   805.7 1188.95   815.5 1190.75   835.1 1201.44
#Mann= 3 , 0 , 0
       0     0.1       0   471.1   0.045       0   486.1     0.1       0
Bank Sta=   471.1,   486.1
Exp/Cntr=0.3,0.1

Type RM Length L Ch R = 1 ,2386.1,282.032,279.345,276.531
XS GIS Cut Line= 3
     1698445.787      355734.988     1698085.369      355464.851
     1697667.280      355226.708
#Sta/Elev= 30
       0 1209.25    39.2 1197.85    58.8 1190.32    78.3 1186.06    97.9 1178.57
   117.5 1174.28   137.1 1166.81   156.7 1162.73   176.3 1155.21   186.0 1154.47
   264.4 1123.75   293.8 1108.05   342.7 1087.16   362.3 1075.93   401.5 1062.84
   416.8 1060.13   430.8 1059.71   431.8 1059.92   450.4 1062.98   519.2 1067.29
   578.1 1076.06   617.3 1084.46   656.6 1103.45   695.9 1118.99   705.7 1121.05
   754.8 1142.57   774.5 1147.70   823.6 1170.31   843.2 1175.45   931.6 1213.69
#Mann= 3 , 0 , 0
       0     0.1       0   416.8   0.045       0   431.8     0.1       0
Bank Sta=   416.8,   431.8
Exp/Cntr=0.3,0.1

Type RM Length L Ch R = 1 ,2106.8,397.652,400,399.9
XS GIS Cut Line= 3
     1698686.766      355496.742     1698260.820      355272.365
     1697677.180      354979.265
#Sta/Elev= 30
       0 1265.42    19.7 1259.67    29.5 1254.19    39.3 1252.43    59.0 1243.42
   108.1 1229.10   117.9 1223.16   176.9 1202.65   226.0 1177.75   245.6 1173.01
   275.1 1160.53   324.2 1134.89   373.4 1114.13   402.8 1098.01   422.5 1090.86
   473.9 1058.59   488.9 1056.45   491.2 1056.43   510.7 1059.71   549.7 1059.80
   569.2 1062.99   617.9 1063.46   764.1 1093.88   793.4 1102.52   812.9 1110.84
   861.6 1124.71   910.3 1145.71  1037.1 1187.33  1085.8 1208.17  1134.5 1222.63
#Mann= 3 , 0 , 0
       0     0.1       0   473.9   0.045       0   488.9     0.1       0
Bank Sta=   473.9,   488.9
Exp/Cntr=0.3,0.1

Type RM Length L Ch R = 1 ,1706.8,500.042,485.194,473.915
XS GIS Cut Line= 3
     1698778.086      355238.004     1698307.400      354917.523
     1697778.646      354649.501
#Sta/Elev= 30
       0 1190.59    29.5 1187.19    88.4 1167.36   117.8 1163.59   127.6 1159.21
   157.1 1154.14   216.0 1134.48   255.3 1124.84   284.7 1111.65   304.4 1107.18
   353.4 1086.02   373.1 1080.61   402.5 1066.67   471.3 1059.97   530.2 1059.71
   559.6 1056.43   561.9 1056.43   576.9 1058.29   656.9 1076.43   724.9 1109.51
   744.4 1122.83   763.8 1131.55   822.1 1166.01   851.3 1175.70   909.6 1200.05
   938.7 1208.18   987.3 1230.23  1006.7 1236.73  1035.9 1252.29  1162.2 1301.30
#Mann= 3 , 0 , 0
       0     0.1       0   561.9   0.045       0   576.9     0.1       0
Bank Sta=   561.9,   576.9
Exp/Cntr=0.3,0.1

Type RM Length L Ch R = 1 ,1221.6,575.401,570.663,591.676
XS GIS Cut Line= 3
     1699170.200      354443.898     1698453.140      354482.414
     1697968.780      354492.412
#Sta/Elev= 30
       0 1231.14    68.9 1215.51   147.6 1182.48   196.7 1170.50   216.4 1161.76
   255.8 1150.88   314.8 1127.83   393.5 1091.73   423.0 1082.50   501.7 1072.34
   570.5 1059.61   609.9 1056.43   707.1 1056.43   722.1 1056.43   737.5 1056.90
   766.5 1069.13   785.9 1087.58   805.3 1096.67   815.0 1104.12   824.7 1105.88
   853.7 1128.03   882.8 1141.43   902.2 1154.87   950.6 1179.36   970.0 1194.03
   999.1 1208.94  1057.2 1226.33  1125.0 1242.90  1163.8 1250.31  1202.6 1250.81
#Mann= 3 , 0 , 0
       0     0.1       0   707.1   0.045       0   722.1     0.1       0
Bank Sta=   707.1,   722.1
Exp/Cntr=0.3,0.1

Type RM Length L Ch R = 1 ,650.9,210.861,264.736,195.892
XS GIS Cut Line= 4
     1699174.085      354144.144     1698750.183      354017.876
     1698331.477      354128.378     1697956.493      354351.586
#Sta/Elev= 30
       0 1234.86    49.1 1218.74    98.3 1196.79   147.4 1179.70   196.6 1155.82
   206.4 1154.03   226.1 1141.46   255.6 1127.61   383.3 1080.44   403.0 1074.84
   412.8 1069.78   442.3 1060.84   471.2 1055.02   528.9 1049.87   532.9 1049.87
   547.9 1049.87   711.8 1049.96   731.0 1053.15   808.0 1056.43   865.7 1064.84
   904.4 1082.17   943.2 1103.85   962.6 1117.99   991.7 1132.51  1011.1 1139.35
  1127.5 1164.07  1166.3 1176.01  1185.7 1179.32  1263.3 1200.15  1311.7 1207.00
#Mann= 3 , 0 , 0
       0     0.1       0   532.9   0.045       0   547.9     0.1       0
Bank Sta=   532.9,   547.9
Exp/Cntr=0.3,0.1

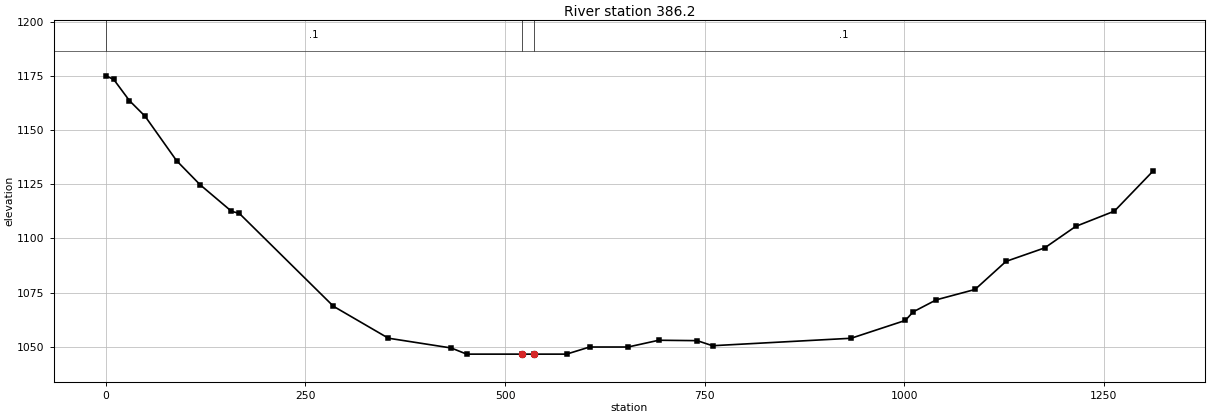
Type RM Length L Ch R = 1 ,386.2,268.125,386.176,368.005
XS GIS Cut Line= 4
     1699073.837      354040.764     1698659.501      353885.966
     1698234.251      353967.745     1697844.959      354164.940
#Sta/Elev= 30
       0 1174.97     9.8 1173.31    29.5 1163.51    49.1 1156.31    88.5 1135.84
   117.9 1124.76   157.3 1112.49   167.1 1111.51   285.0 1068.67   353.8 1053.94
   432.5 1049.43   451.9 1046.59   520.9 1046.59   535.9 1046.59   577.0 1046.59
   605.9 1049.87   654.0 1049.87   692.5 1052.99   740.6 1052.81   759.9 1050.47
   933.5 1053.91  1001.4 1062.14  1011.1 1066.06  1040.2 1071.64  1088.7 1076.42
  1127.5 1089.37  1176.0 1095.60  1214.8 1105.51  1263.3 1112.56  1311.7 1131.05
#Mann= 3 , 0 , 0
       0     0.1       0   520.9   0.045       0   535.9     0.1       0
Bank Sta=   520.9,   535.9
Exp/Cntr=0.3,0.1